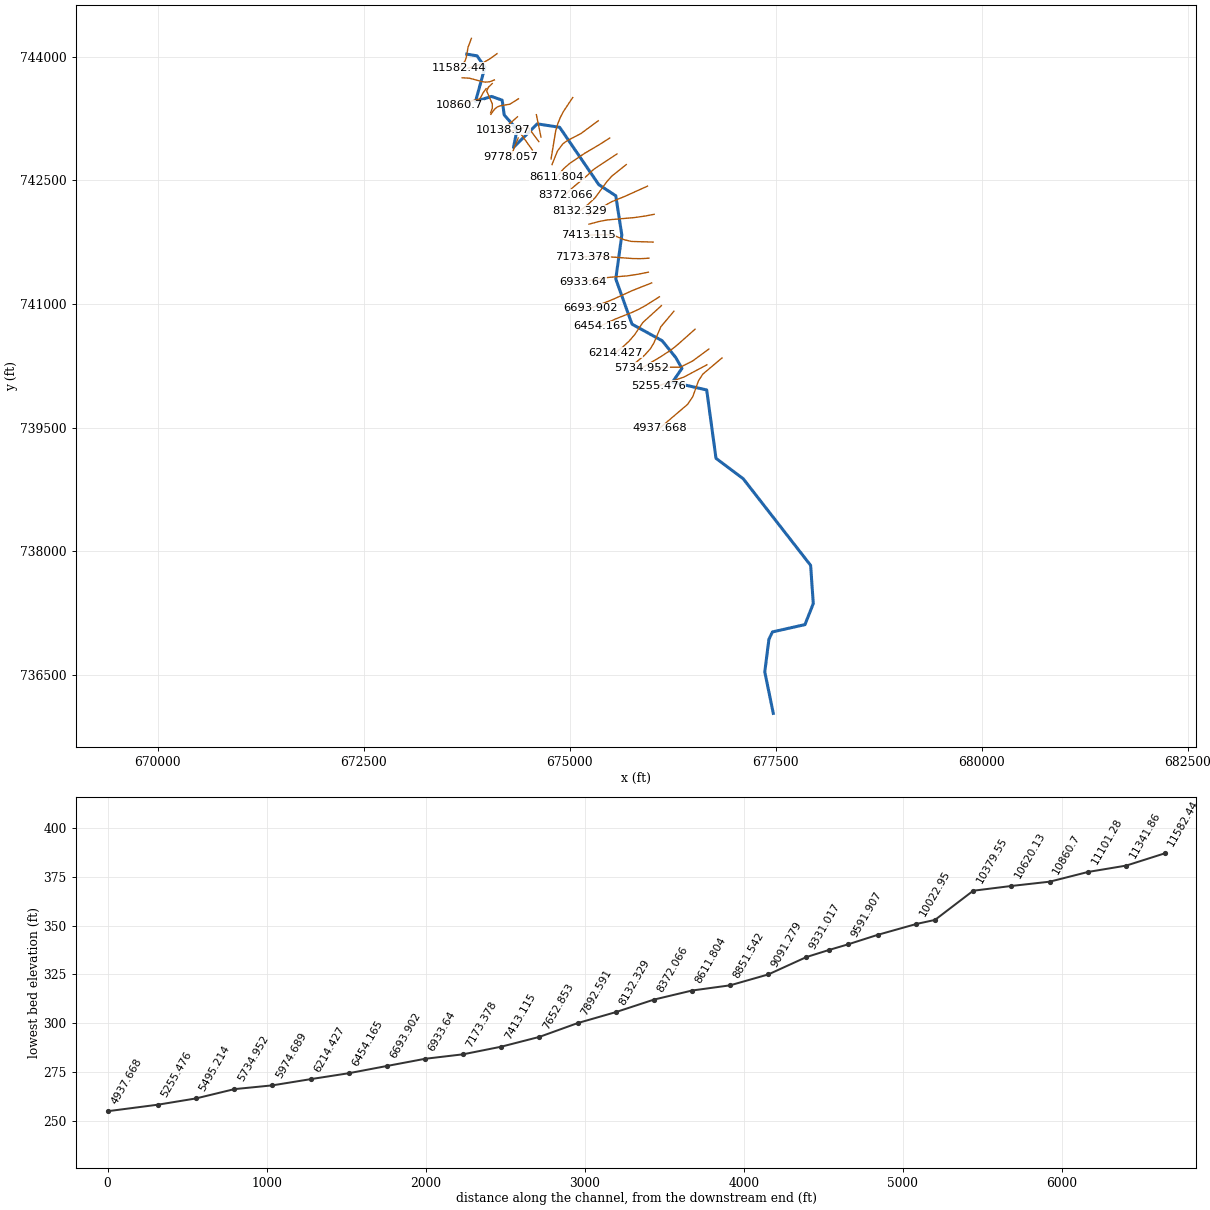
--- 4023_ras.prj (project) ---

Proj Title=4023
Current Plan=p01
Default Exp/Contr=0.3,0.1
English Units
Geom File=g01
Flow File=f01
Plan File=p01
Y Axis Title=Elevation
X Axis Title(PF)=Main Channel Distance
X Axis Title(XS)=Station
BEGIN DESCRIPTION:
RFD model 4023 exported to HEC-RAS
END DESCRIPTION:

--- 4023_ras.p01 (plan) ---

Plan Title=Plan 01
Program Version=4.10
Short Identifier=Plan 01
Geom File=g01
Flow File=f01
Subcritical Flow
Calc Critical at every XS
Secant Critical Depth

--- 4023_ras.f01 (steady flow) ---

Flow Title=Flow 01
Program Version=5.01
Number of Profiles= 6
Profile Names=10yr,25yr,50yr,100yr,100plus,500yr
River Rch & RM=4023,40,11582.44
  1890.9 3329.42 4794.76 6268.77 9152.4112389.74
River Rch & RM=4023,40,11341.86
 1892.37 3332.34 4799.28 6275.04 9161.5512401.97
River Rch & RM=4023,40,11101.28
 1895.22 3338.05 4808.16 6287.43 9179.64 12426.4
River Rch & RM=4023,40, 10860.7
 1896.69 3340.96 4812.66 6293.67 9188.76 12438.6
River Rch & RM=4023,40,10620.13
 1897.44 3342.47 4815.03 6296.99  9193.612445.18
River Rch & RM=4023,40,10379.55
 1898.19 3343.99  4817.4  6300.3 9198.4412451.75
River Rch & RM=4023,40,10138.97
 1898.73 3345.07 4819.09 6302.67 9201.8912456.44
River Rch & RM=4023,40,10022.95
 1900.66 3348.97 4825.17 6311.18 9214.3312473.33
River Rch & RM=4023,40,9778.057
 2000.76 3537.56 5108.65 6695.56 9775.5113182.05
River Rch & RM=4023,40,9591.907
 2001.26 3538.59 5110.28 6697.85 9778.8713186.64
River Rch & RM=4023,40,9470.575
 2001.67 3539.42 5111.58 6699.69 9781.5513190.31
River Rch & RM=4023,40,9091.279
 2009.27 3554.68 5135.36  6732.9 9830.0413255.39
River Rch & RM=4023,40,8851.542
 2010.22  3556.6 5138.35 6737.09 9836.1513263.63
River Rch & RM=4023,40,8611.804
 2839.12 5066.67 7363.61 9702.1614165.1518334.85
River Rch & RM=4023,40,8372.066
 2841.41 5071.37 7371.06  9712.714180.54   18355
River Rch & RM=4023,40,8132.329
  2847.5 5083.89 7390.83 9740.62 14221.318408.16
River Rch & RM=4023,40,7892.591
  2852.6 5094.69 7408.13 9765.3614257.4218456.43
River Rch & RM=4023,40,7652.853
 2856.91 5103.83 7422.81 9786.3514288.0718497.42
River Rch & RM=4023,40,7413.115
 2860.45 5111.28 7434.71 9803.3214312.8418530.35
River Rch & RM=4023,40,7173.378
 2862.86 5116.41 7442.98 9815.1814330.1618553.63
River Rch & RM=4023,40, 6933.64
 2870.13 5131.47 7466.88 9849.0714379.6418618.58
River Rch & RM=4023,40,6693.902
 2873.53 5138.73 7478.56 9865.8214404.0918651.43
River Rch & RM=4023,40,6454.165
 2875.27 5142.51 7484.71 9874.6914417.0418669.04
River Rch & RM=4023,40,6214.427
 2877.06 5146.43 7491.09 9883.9114430.5118687.45
River Rch & RM=4023,40,5974.689
 2880.03  5152.9 7501.63 9899.1614452.7818717.85
River Rch & RM=4023,40,5734.952
 2882.29 5157.84 7509.67 9910.7914469.7518741.03
River Rch & RM=4023,40,5495.214
 2886.97 5168.12 7526.46 9935.14 14505.318789.76
River Rch & RM=4023,40,5255.476
 2888.18 5170.79 7530.84  9941.514514.5818802.54
River Rch & RM=4023,40,4937.668
 3014.28 5422.71 7923.0310489.2415314.2919814.53
River Rch & RM=4023,40,4721.424
 3016.46 5427.57 7931.02 10500.915331.3219837.98
River Rch & RM=4023,40,4408.637
  3017.6 5430.13 7935.2510507.0915340.3519850.49
River Rch & RM=4023,40,4300.311
 3047.73 5495.04 8040.3910658.6515561.6320148.13
River Rch & RM=4023,40,3903.208
 3048.01 5495.67 8041.4410660.1915563.8820151.23
Boundary for River Rch & Prof#=4023,40,1
Up Type= 0
Dn Type= 2
Boundary for River Rch & Prof#=4023,40,2
Up Type= 0
Dn Type= 2
Boundary for River Rch & Prof#=4023,40,2
Up Type= 0
Dn Type= 2
Boundary for River Rch & Prof#=4023,40,2
Up Type= 0
Dn Type= 2
Boundary for River Rch & Prof#=4023,40,2
Up Type= 0
Dn Type= 2
Boundary for River Rch & Prof#=4023,40,2
Up Type= 0
Dn Type= 2

--- 4023_ras.g01 (geometry) ---

Geom Title=4023
Program Version=4.10

River Reach=4023,40
Reach XY= 30
673748.597945929744031.132442102673874.118779302744010.299108759
673969.952112615743872.799108773673855.889612585743456.653275445
674050.681279272743518.111608773674179.327112615743471.757442087
674204.327112615743292.069942087674359.535445958743116.549108759
674316.827112615742899.361608759674604.847945958743184.778275445
674876.722945958743143.111608759675351.202112585742447.799108773
675557.972945958742311.861608773675630.889612615741835.819942087
675557.972945958741301.965775445675754.327112585740754.569942087
676120.472945929740553.007442102676286.097945929740348.319942102
676360.577112615740217.069942102676245.472945929740050.403275415
676661.097945929739955.611608773 676774.04689762739126.167582512
677103.908008754738878.771749198 677922.48439762737826.688415855
677954.602453142737363.146749198677853.908008724 737107.93841587
677459.810786515737019.396749184677416.408008754736930.855082512
677366.060786515736534.153693646 677469.35939762736030.681471422

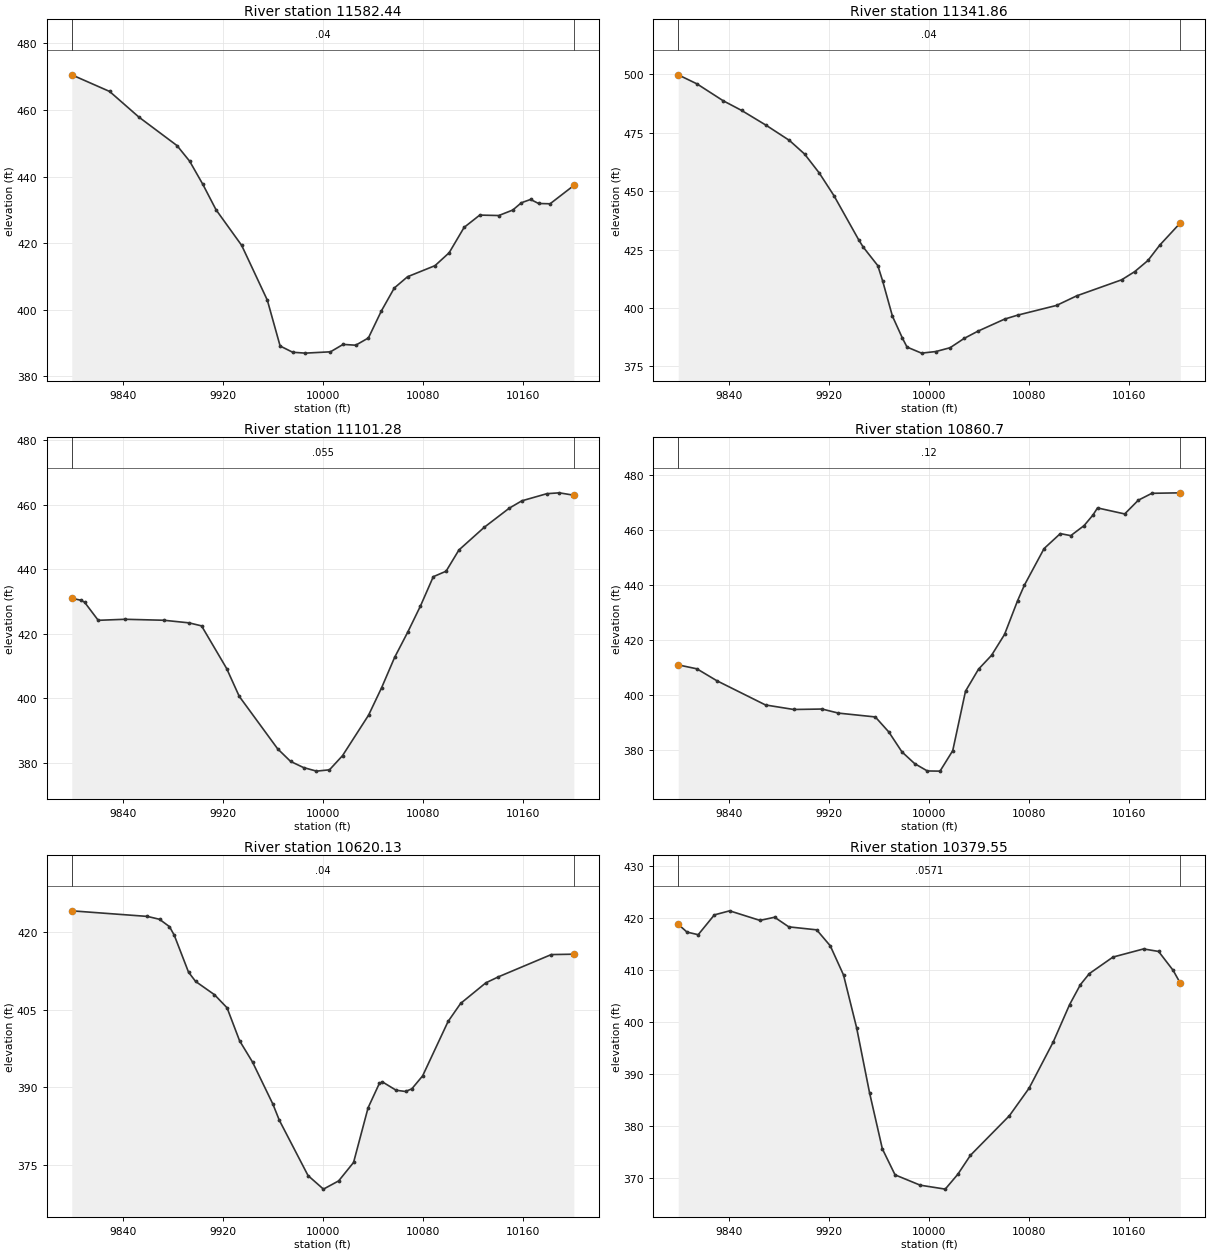
Type RM Length L Ch R = 1 ,11582.44,240.579000,240.579000,240.579000
XS GIS Cut Line= 6
673805.936182076744222.900578539673765.029581063744114.871433686
673744.825967243743996.923579479673731.019316777743953.676076632
673697.866945449743902.843372929673652.847786941 743863.20772918
#Sta/Elev= 30
9799.066470.56859829.355465.56919852.855457.8469 9883.31449.29869893.434444.5962
9903.981437.63839914.529430.00759935.047419.30419955.561402.85929965.813389.0688
9975.887387.19019985.961386.930410006.11387.327910016.21389.551510026.31389.3097
10036.46391.493310046.82399.594110057.17406.499910067.79409.889410089.75413.2154
10101.07417.089610113.06424.724910125.58428.417210140.81428.283910151.99429.9311
10158.85432.114810166.25433.116110172.63431.903910181.86431.812810200.87437.3206
#Mann= 3 , 0 , 0
9799.066    0.04       09799.066    0.04       010200.87    0.04       0
#XS Ineff= 2 , 0
       0                               0
Bank Sta=9799.066,10200.87
Exp/Cntr=0.3,0.1

Type RM Length L Ch R = 1 ,11341.86,240.579000,240.579000,240.579000
XS GIS Cut Line= 6
674116.916195531744036.827719432674033.167438758743976.344653204
673926.643056571743913.313046772673895.033811773 743900.40986119
673817.388656169743878.921533668673760.460662871743859.719286141
#Sta/Elev= 30
9799.017499.81289814.018495.94049834.952488.73199849.721484.58159869.278478.2614
9888.032471.73619900.141  465.929911.926 457.7869923.639448.13029943.355429.3158
9947.065426.10889958.778 418.1459962.561411.74999970.491396.51789978.539387.0551
9982.167383.29649993.764380.703210005.27381.385810016.65383.016710027.93387.0073
10038.74390.0549 10060.3395.266810070.71396.959310101.84401.116710118.08 405.239
10153.94412.073410164.49415.607610175.05420.359210184.42426.884210200.94436.4217
#Mann= 3 , 0 , 0
9799.017    0.04       09799.017    0.04       010200.94    0.04       0
#XS Ineff= 2 , 0
       0                               0
Bank Sta=9799.017,10200.94
Exp/Cntr=0.3,0.1

Type RM Length L Ch R = 1 ,11101.28,240.579000,240.579000,240.579000
XS GIS Cut Line= 6
674084.350163029743717.871872235674028.393610295743696.227780875
673975.817983603743691.257272593673930.203749599 743699.11040566
673781.573426551743739.154040099673693.408253209743744.046502793
#Sta/Elev= 30
9799.085431.04919806.161430.46579809.315  429.849820.256 424.2189841.673424.5376
9872.778424.23489892.957423.42559902.959422.49149923.043409.26649933.118400.6384
9963.867384.3521 9974.23380.44569984.593 378.5389994.956377.433810005.35377.8407
10015.77382.226710036.61394.783310047.03403.269510057.45412.687510067.87420.4651
10078.17428.666810088.43437.743910098.68439.450610108.94 446.02910129.13453.0448
10149.25459.005410159.31461.282810179.33463.496810189.33463.763610200.93463.0164
#Mann= 3 , 0 , 0
9799.085   0.055       09799.085   0.055       010200.93   0.055       0
#XS Ineff= 2 , 0
       0                               0
Bank Sta=9799.085,10200.93
Exp/Cntr=0.3,0.1

Type RM Length L Ch R = 1 , 10860.7,240.578900,240.578900,240.578900
XS GIS Cut Line= 6
673984.368916161743611.952767642673948.760917536743563.635864928
673916.945800677743503.446345933673901.315924015743487.153363294
673781.411403177743455.611144957673664.092765078743408.379984103
#Sta/Elev= 30
  9799.2411.06379814.147409.63599830.126405.30389869.044396.50319891.666394.8612
9914.289395.02659927.357393.54769956.902392.15219967.703386.68929978.225379.4506
9988.379375.19429998.532372.526810008.69372.464410018.85379.898910029.08401.5215
10039.49409.5135 10049.9414.537710060.31422.134110070.72434.365110076.21440.0496
10091.96453.341410104.93458.7698 10113.3458.028410123.96461.674110131.04465.5098
 10134.7 468.10210156.46465.913410167.34470.905510178.22473.412210200.96473.5861
#Mann= 3 , 0 , 0
  9799.2    0.12       0  9799.2    0.12       010200.96    0.12       0
#XS Ineff= 2 , 0
       0                               0
Bank Sta=9799.2,10200.96
Exp/Cntr=0.3,0.1

Type RM Length L Ch R = 1 ,10620.13,240.579000,240.579000,240.579000
XS GIS Cut Line= 6
674058.519466974743674.604540973674011.611625157743628.831356304
673991.705729751743582.687885995674059.641687067743427.375664523
674059.218911743743374.710633453674038.641867262 743318.40673988
#Sta/Elev= 30
9799.235424.18289859.797423.0983 9869.42422.54219877.385421.1183 9881.21419.4613
9892.608 412.3139898.272410.50819913.385407.93399923.451405.39679933.468 399.012
9943.841394.87519960.127386.72669965.261383.6119 9988.23372.894810000.54370.2694
10012.73371.866610024.64375.435710036.24386.014210045.29390.760710047.72391.0438
10058.67389.427610066.24389.182810071.27389.708110079.88392.208110100.25402.7524
10110.29406.248610130.41410.227310140.49411.395510182.78415.707710200.84415.7823
#Mann= 3 , 0 , 0
9799.235    0.04       09799.235    0.04       010200.84    0.04       0
#XS Ineff= 2 , 0
       0                               0
Bank Sta=9799.235,10200.84
Exp/Cntr=0.3,0.1

Type RM Length L Ch R = 1 ,10379.55,240.579000,240.579000,240.579000
XS GIS Cut Line= 6
674377.361422254743489.428858585674272.195561186 743423.55082457
674156.519758551743404.241350216674120.661296689743390.751701297
674083.905956123743359.910989202674041.795418762743300.577043032
#Sta/Elev= 30
9799.073418.79899806.065 417.3049815.048416.8028 9827.97 420.6129840.219421.3951
9864.486419.54979876.176420.16189887.564418.30899909.877417.73449920.747414.6585
9931.351409.0468 9941.85398.87429952.207386.34929962.437 375.5799972.601370.5753
9992.701368.589510012.76 367.828 10022.8370.678710032.92 374.33910064.14 381.967
10079.93387.281110099.15396.136810112.29403.345710120.94407.188910128.09409.3125
   10147412.495410171.46414.059510183.51413.576610195.14409.942810200.89407.4614
#Mann= 3 , 0 , 0
9799.073  0.0571       09799.073  0.0571       010200.89  0.0571       0
#XS Ineff= 2 , 0
       0                               0
Bank Sta=9799.073,10200.89
Exp/Cntr=0.3,0.1

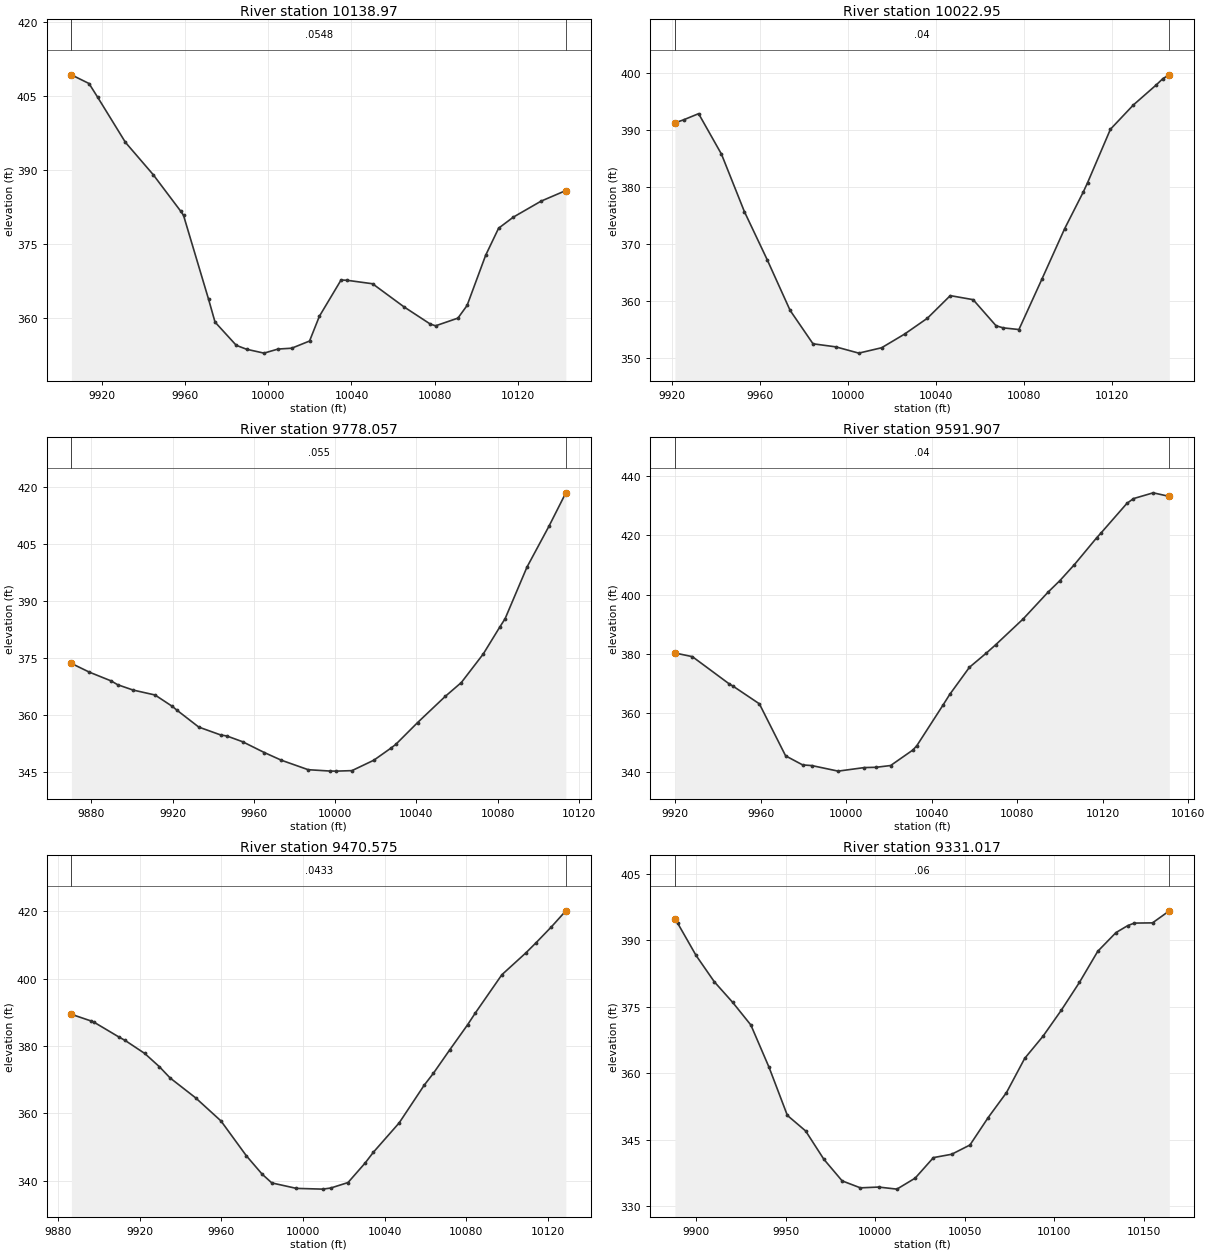
Type RM Length L Ch R = 1 ,10138.97,116.017400,116.017400,116.017400
XS GIS Cut Line= 2
674364.512273312743270.591349557674186.058064193743113.659256086
#Sta/Elev= 29
9905.384409.32469913.851407.56399918.051404.75299931.368395.62549944.684389.0891
9958.001381.6285 9959.28380.81629971.318 363.8059974.423359.17949984.634354.4626
9989.566353.67159997.951352.882110004.71353.709410011.27353.879610019.85355.3369
10024.58 360.36310034.99367.7092 10037.9367.654910050.14366.951210065.28362.2543
10077.85358.784210080.42358.423210091.17359.983810095.57362.553810104.48372.7169
10110.71378.2167 10117.8380.465210131.12383.704110143.03385.8574
#Mann= 3 , 0 , 0
9905.384  0.0548       09905.384  0.0548       010143.03  0.0548       0
#XS Ineff= 2 , 0
       0                10047.62       0
Bank Sta=9905.384,10143.03
Exp/Cntr=0.3,0.1

Type RM Length L Ch R = 1 ,10022.95,244.893700,244.893700,244.893700
XS GIS Cut Line= 2
674435.355904102 743136.07812658674219.237992555743074.202044025
#Sta/Elev= 28
9921.241391.28329921.612391.27419925.158391.75539932.013392.84139942.415385.7334
9952.817375.66659963.219367.1987 9973.62358.32549984.022352.46289994.424351.9243
10004.83350.825910015.23351.769410025.63 354.16110036.03356.950610046.43360.9153
10056.83360.206910067.24355.630610070.48355.259410077.64354.966310088.04363.7637
10098.44372.666210106.81379.022210108.84380.715610119.25390.110410129.65394.3585
10140.05397.876610143.14399.007710146.04399.6562
#Mann= 3 , 0 , 0
9921.241    0.04       09921.241    0.04       010146.04    0.04       0
#XS Ineff= 2 , 0
       0                10050.45       0
Bank Sta=9921.241,10146.04
Exp/Cntr=0.3,0.1

Type RM Length L Ch R = 1 ,9778.057,186.150000,186.150000,186.150000
XS GIS Cut Line= 2
674373.479821563743013.222716272674282.907584727742787.240501717
#Sta/Elev= 30
9870.144373.59739879.002371.29369889.776368.97269892.937367.98059900.549366.5765
9911.322365.27999919.817362.28749922.096361.28259932.869356.82499943.642354.7547
9946.697354.48159954.415352.97279965.189350.10749973.577348.08729986.735345.5996
9997.508345.241910000.46345.223410008.28345.354510019.06348.099710027.34351.2319
10029.83352.2508 10040.6358.013610054.22364.909810062.15368.563910072.92376.0693
 10081.1383.195510083.69385.372310094.47398.971110105.24409.6856 10113.6418.5309
#Mann= 3 , 0 , 0
9870.144   0.055       09870.144   0.055       0 10113.6   0.055       0
#XS Ineff= 2 , 0
       0                               0
Bank Sta=9870.144,10113.6
Exp/Cntr=0.3,0.1

Type RM Length L Ch R = 1 ,9591.907,121.332000,121.332000,121.332000
XS GIS Cut Line= 2
 674410.24676913743057.163702458674544.759992123742868.845190302
#Sta/Elev= 29
9919.758380.27289927.936379.03329945.141  369.859946.995369.05529959.284363.1012
9971.573345.5248 9979.55342.46259983.862342.23929996.151340.364110008.44341.5657
10013.96341.661910020.73 342.25910031.16347.509710033.02 348.99810045.31362.7515
10048.37366.2638 10057.6375.436510065.57  380.2710069.89383.048710082.78391.7917
10094.46400.862910099.98404.747710106.75410.135710117.19419.215310119.04420.6753
10131.33430.822510134.39432.422610143.62434.370410151.18433.1585
#Mann= 3 , 0 , 0
9919.758    0.04       09919.758    0.04       010151.18    0.04       0
#XS Ineff= 2 , 0
       0                               0
Bank Sta=9919.758,10151.18
Exp/Cntr=0.3,0.1

Type RM Length L Ch R = 1 ,9470.575,139.557900,139.557900,139.557900
XS GIS Cut Line= 2
674479.296890289743163.877526015674623.674416244742969.281730115
#Sta/Elev= 30
9886.551389.41199896.123 387.4439897.606387.07389910.057382.58759912.906 381.636
9922.509377.76459929.689373.82899934.961370.47449947.413364.59169959.864357.7092
9972.316347.34279980.037341.89569984.768339.2962 9996.82337.669210009.67337.4499
 10013.6337.770410022.12339.405810030.39345.131310034.58348.441610047.17357.1293
10059.48 368.36810063.95371.882110071.93378.814910080.73386.315210084.38389.6971
10097.52401.180110109.29407.6778 10114.3410.701910121.74415.373110128.86420.1662
#Mann= 3 , 0 , 0
9886.551  0.0433       09886.551  0.0433       010128.86  0.0433       0
#XS Ineff= 2 , 0
       0                               0
Bank Sta=9886.551,10128.86
Exp/Cntr=0.3,0.1

Type RM Length L Ch R = 1 ,9331.017,239.737700,239.737700,239.737700
XS GIS Cut Line= 2
674594.081507176743296.597239316674649.680306017743025.777283758
#Sta/Elev= 30
9887.959394.83319889.589393.75239899.798386.54289910.007380.60139920.215375.9917
9930.424370.87039940.632361.30279950.841350.49339961.049346.99519971.258340.6017
9981.467335.73999991.675334.168110001.88334.345310012.09333.8792 10022.3336.3568
10032.51340.983510042.72341.738310052.93343.825910063.14350.020210073.34355.6285
10083.55363.351910093.76368.331710103.97 374.17810114.18380.496710124.39387.4801
10134.59391.700810141.15393.2654 10144.8393.835210155.01393.888110164.43396.6007
#Mann= 3 , 0 , 0
9887.959    0.06       09887.959    0.06       010164.43    0.06       0
#XS Ineff= 2 , 0
       0                               0
Bank Sta=9887.959,10164.43
Exp/Cntr=0.3,0.1

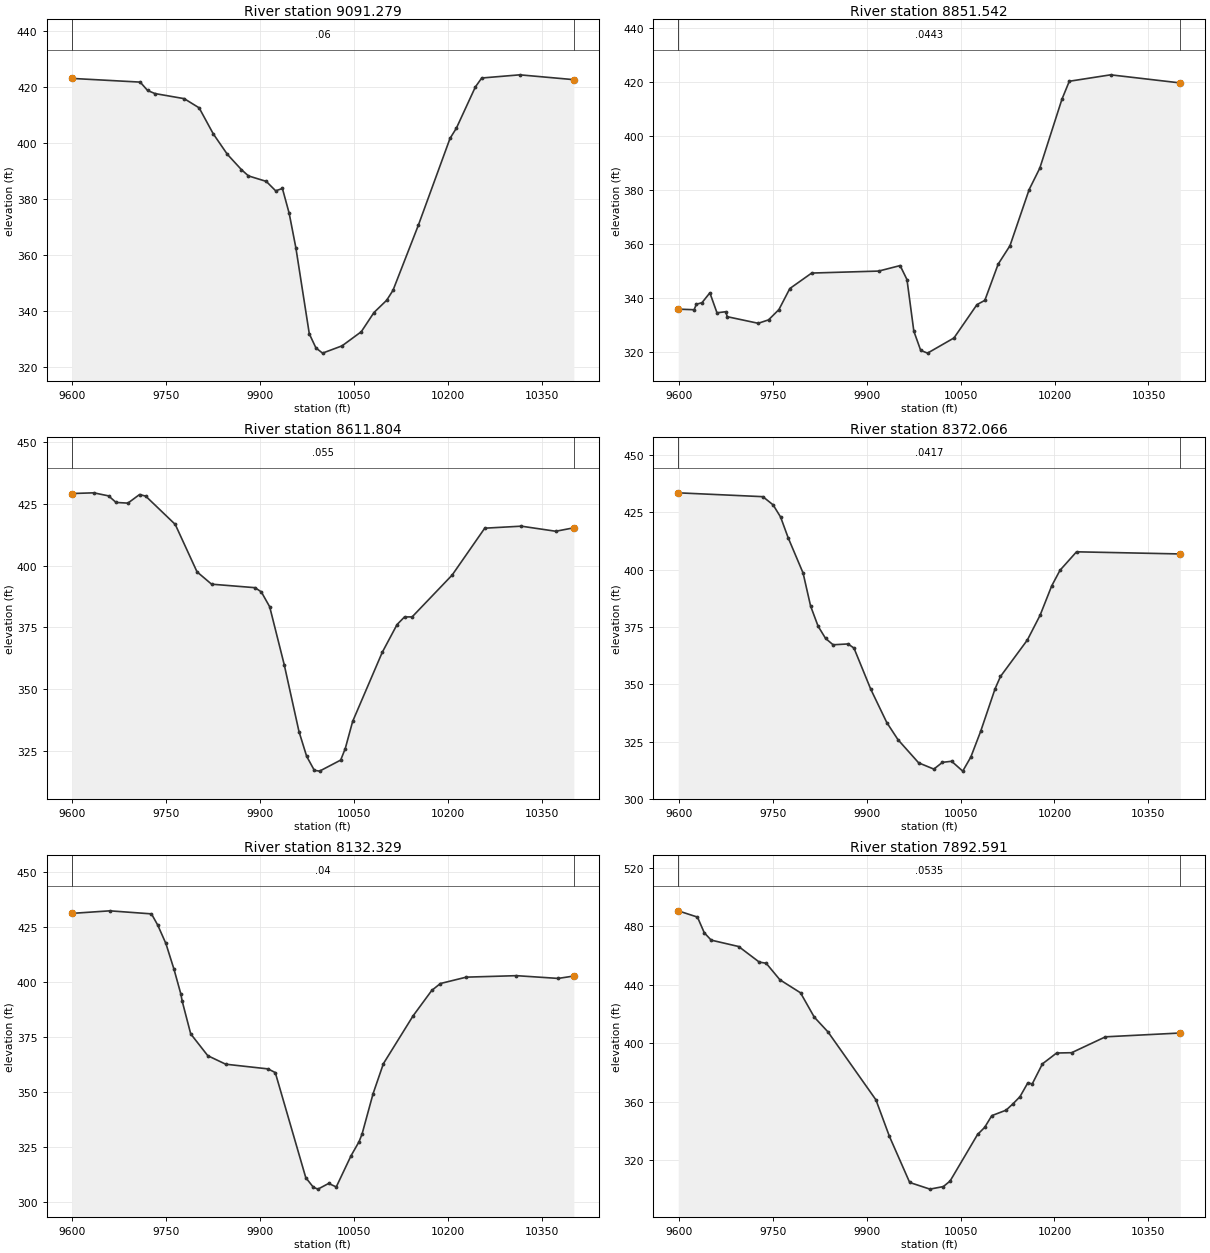
Type RM Length L Ch R = 1 ,9091.279,239.737700,239.737700,239.737700
XS GIS Cut Line= 6
675035.145634131743504.224185717674921.985717006743334.225518822
674882.370336167 743257.25122824674852.822205952743183.709029642
674829.129346621743101.475051094674772.494018081742760.120435878
#Sta/Elev= 30
 9599.09423.00479708.405421.68129720.167418.69719731.929417.59529778.692415.7772
9802.501412.49949825.034403.23859847.528395.92899870.021390.45759881.268388.2188
9909.752386.2557 9924.74382.89959935.517383.72269946.294374.89519957.071 362.482
9978.459331.87049989.047326.83759999.633324.982510030.79327.580910061.48332.6184
10081.73339.468610101.98343.8343 10112.1347.3724 10152.6370.606910203.22401.5993
10213.35405.242410243.72419.966710253.84 423.14410314.65424.279310400.97422.5537
#Mann= 3 , 0 , 0
 9599.09    0.06       0 9599.09    0.06       010400.97    0.06       0
#XS Ineff= 2 , 0
       0                               0
Bank Sta=9599.09,10400.97
Exp/Cntr=0.3,0.1

Type RM Length L Ch R = 1 ,8851.542,239.737700,239.737700,239.737700
XS GIS Cut Line= 6
675345.131075248743222.582176367675133.182367152743066.085209062
674966.968116143 742980.22354348674913.518924816742940.790473408
674848.888141759742852.758490865674783.837388996742690.806922461
#Sta/Elev= 30
9599.056335.73019624.397335.51299628.003 337.5419636.985338.12249649.573341.7794
9660.931334.37429674.749334.76719677.395 332.9279726.788330.48259743.252331.7475
9759.836335.56889777.275343.37799812.152349.11419919.179349.85179953.406351.8888
9964.353346.68949975.299 327.5589986.246320.44169997.193319.4143 10039.4325.0423
10076.07 337.39410088.69 338.99410109.97352.432410128.84359.266710159.47380.0992
10176.45388.029610211.83 413.61310223.58420.265710289.56422.649610400.85  419.64
#Mann= 3 , 0 , 0
9599.056  0.0443       09599.056  0.0443       010400.85  0.0443       0
#XS Ineff= 2 , 0
       09935.651                       0
Bank Sta=9599.056,10400.85
Exp/Cntr=0.3,0.1

Type RM Length L Ch R = 1 ,8611.804,239.737700,239.737700,239.737700
XS GIS Cut Line= 6
675484.653006733743013.104441272675354.215057602742930.143513682
675180.762453011742828.119623591675002.276113513742707.688304979
674924.104972922742640.247276178674843.121627183742542.116962472
#Sta/Elev= 30
9599.043429.22469634.185429.51069657.888428.26889669.739425.61569688.678425.3377
9707.312428.82459717.144428.17399764.319416.70369799.124397.48399822.327392.4987
9891.936391.07129901.842389.3399 9915.14383.34329938.343359.90049961.923332.8002
9974.179322.75949986.435 317.074 9994.85316.748710028.51321.221710035.82325.8731
10047.65336.895810094.94364.894510118.59376.142810130.48379.224210142.64379.2402
10206.61396.207110258.62 415.18410317.05415.9993 10372.1413.936610400.93415.3432
#Mann= 3 , 0 , 0
9599.043   0.055       09599.043   0.055       010400.93   0.055       0
#XS Ineff= 2 , 0
       0                               0
Bank Sta=9599.043,10400.93
Exp/Cntr=0.3,0.1

Type RM Length L Ch R = 1 ,8372.066,239.737700,239.737700,239.737700
XS GIS Cut Line= 6
675571.575770231 742819.33785136675325.195592442742657.159847786
675279.658546361742624.601365105675207.636281818742555.271982942
675035.956880507742412.145065555674943.644200216742324.341326607
#Sta/Elev= 30
9599.033433.48789734.237431.81049750.569428.23289762.541422.93089774.513 413.951
9798.457398.48939810.429384.12589822.401375.32329834.373369.97929846.345367.2086
9870.289367.57119879.739365.75679906.532 347.8259932.099 333.3049949.978325.8312
9983.079315.696510007.31 312.98210021.07315.928410035.72316.392310053.43 312.093
10066.34318.221410082.09329.457610105.06 347.98410113.73353.386410156.69 369.298
   10177 380.086 10195.6392.9259 10208.8 399.70210235.21407.760910400.97406.8239
#Mann= 3 , 0 , 0
9599.033  0.0417       09599.033  0.0417       010400.97  0.0417       0
#XS Ineff= 2 , 0
       0                               0
Bank Sta=9599.033,10400.97
Exp/Cntr=0.3,0.1

Type RM Length L Ch R = 1 ,8132.329,239.737700,239.737700,239.737700
XS GIS Cut Line= 6
675684.794068566742690.969810437675509.436793625742550.628904278
675450.500015803742484.476738153675307.988673844 742288.71363181
675221.756377135742207.215415078675120.329716729742130.243440863
#Sta/Elev= 30
9599.063430.99039659.878 432.1599726.352430.77669736.345425.68299749.339417.3439
9762.333405.61099773.334394.3069 9775.39391.14399789.033376.24099816.318 366.319
9844.917362.45679912.559360.32429924.102358.64789972.822310.89279985.003306.5005
9992.256305.684410009.35 308.27110021.49306.679410045.09 320.854 10057.9327.2405
10062.73330.744310080.34349.095910096.79362.706210144.13384.402910174.06395.9951
10187.78399.117110229.11402.018910309.33402.690710375.95401.444110400.96402.5308
#Mann= 3 , 0 , 0
9599.063    0.04       09599.063    0.04       010400.96    0.04       0
#XS Ineff= 2 , 0
       0                               0
Bank Sta=9599.063,10400.96
Exp/Cntr=0.3,0.1

Type RM Length L Ch R = 1 ,7892.591,239.737700,239.737700,239.737700
XS GIS Cut Line= 6
675942.949716435742429.457947138675667.459540595742304.837779492
675508.804030909742240.033431729675460.148320388742213.580730585
675311.868167508742125.028009295 675224.08487695742076.942790086
#Sta/Elev= 30
9599.015490.69719629.692486.41369640.667475.62729651.643470.62599695.545466.2478
9728.472455.57619739.447454.80239761.398443.46869794.325 434.5479816.276417.8961
9838.227 407.7459914.811361.20659936.368336.17429968.705304.630910001.05300.0702
 10022.5301.824210033.23 305.60810077.12337.5084 10088.5342.388210099.88350.4124
10122.65354.142910134.17358.7155 10144.9363.407810157.46372.924110164.41 372.099
10180.76385.887610203.41393.306310227.35393.517110281.43404.393910400.97407.0102
#Mann= 3 , 0 , 0
9599.015  0.0535       09599.015  0.0535       010400.97  0.0535       0
#XS Ineff= 2 , 0
       0                               0
Bank Sta=9599.015,10400.97
Exp/Cntr=0.3,0.1

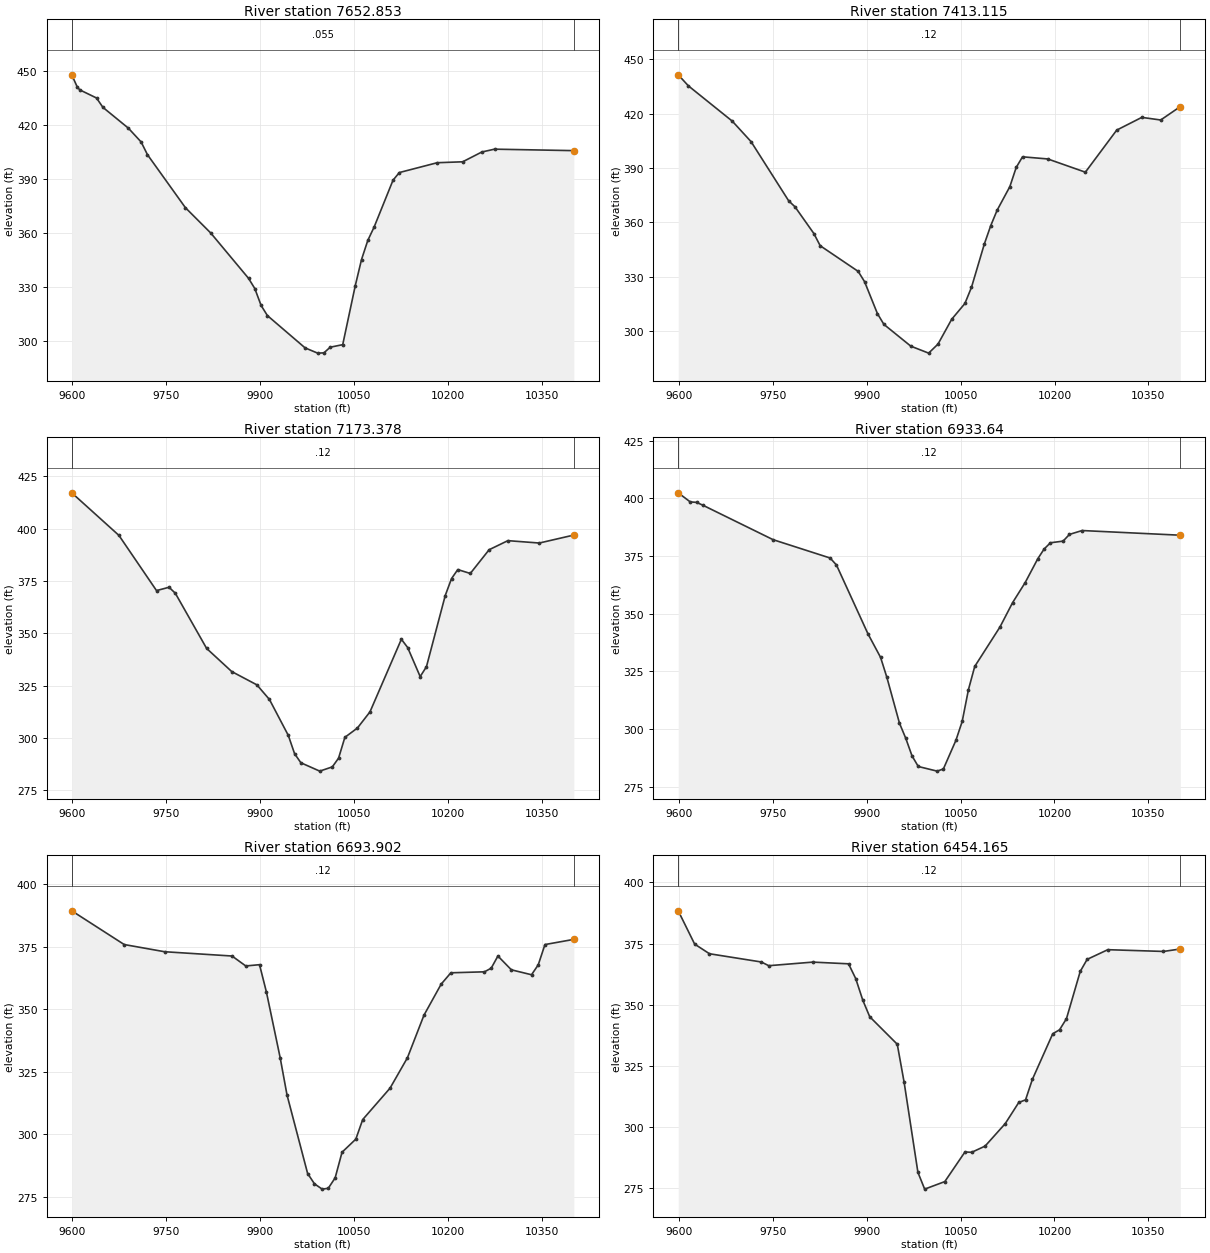
Type RM Length L Ch R = 1 ,7652.853,239.737700,239.737700,239.737700
XS GIS Cut Line= 6
 676023.80490765742087.451747913675916.275658261 742066.81860341
675783.517975349742047.743630342 675457.25448923  742019.0766124
675355.646507677742000.284614964675232.590089568741967.583548127
#Sta/Elev= 30
9599.032447.65829607.998440.72649612.043439.26439638.545434.79269648.728429.6054
9689.457418.01569709.812410.35799719.915403.28989780.531373.84259820.942359.7912
 9881.35334.59599891.399328.89219901.448319.50089911.497313.88179971.688295.9386
 9991.72293.021710001.73293.164210011.75296.303610031.79297.723610051.83330.4893
10061.84345.026210071.86 355.65910081.93363.049410112.13389.1021 10122.2393.3549
10182.73398.821910223.41399.334510253.92404.768410274.26 406.35310400.95405.5333
#Mann= 3 , 0 , 0
9599.032   0.055       09599.032   0.055       010400.95   0.055       0
#XS Ineff= 2 , 0
       0                               0
Bank Sta=9599.032,10400.95
Exp/Cntr=0.3,0.1

Type RM Length L Ch R = 1 ,7413.115,239.737800,239.737800,239.737800
XS GIS Cut Line= 6
676011.252185594741750.194405492675749.262871265741758.015792113
675662.451222317741777.941122784675556.169070706741822.133314691
 675453.91049544741840.608694575675223.891037773741834.931697068
#Sta/Elev= 30
9599.087441.3177 9615.36435.22439685.438415.79149715.438404.49299775.509 371.889
9785.526368.62319815.676353.90069825.751347.18739886.447333.04489896.624 327.391
9917.184 309.7899927.539303.84619970.525291.8426    9999288.009910013.92292.9831
10035.78306.6555 10056.9315.359510067.42324.270810087.91 348.10810098.16  358.24
 10108.4366.763310128.72379.766410138.82390.305310148.92396.155710189.18394.9775
10249.28 387.68910299.31410.8534 10339.4417.876110369.59416.4322 10400.9423.8148
#Mann= 3 , 0 , 0
9599.087    0.12       09599.087    0.12       0 10400.9    0.12       0
#XS Ineff= 2 , 0
       0                               0
Bank Sta=9599.087,10400.9
Exp/Cntr=0.3,0.1

Type RM Length L Ch R = 1 ,7173.378,239.737700,239.737700,239.737700
XS GIS Cut Line= 6
675960.190145323741554.640465329675860.203162215741549.049240628
675765.229371444741550.256666637 675354.73846022741580.387881422
675259.703672526 741578.78720719675160.052304008741569.639147887
#Sta/Elev= 30
9599.043417.15619674.351396.81079734.392370.42169754.394372.00889764.395369.1728
9814.437342.77099854.515331.7152 9894.67325.36139914.753318.36919944.877301.1978
9954.918292.44449964.959288.11069995.083284.112710015.15286.134610025.18 290.324
10035.22300.262510055.28304.721410075.35312.453910125.47347.164210135.49343.2119
10155.51329.308610165.52334.027710195.55368.063210205.56376.147510215.57380.4641
10235.57378.609610265.57 389.94310295.58394.292310345.77393.156310400.94 396.974
#Mann= 3 , 0 , 0
9599.043    0.12       09599.043    0.12       010400.94    0.12       0
#XS Ineff= 2 , 0
       0                               0
Bank Sta=9599.043,10400.94
Exp/Cntr=0.3,0.1

Type RM Length L Ch R = 1 , 6933.64,239.737700,239.737700,239.737700
XS GIS Cut Line= 6
675953.784559285741385.230812805675828.909784464741360.253009307
675697.743043564741339.992989082675485.630546711741323.195771275
675359.791960067741307.696703937675161.127024604741270.266110559
#Sta/Elev= 30
9599.038402.42099618.195398.48979628.393398.28159638.591397.0271 9750.58382.1116
9841.647374.16669851.766371.13819902.103341.2928 9922.22331.10579932.279322.4433
9952.396 302.5849962.417296.05799972.429288.42889982.441283.817610012.48281.8089
 10022.5282.737710042.54295.150810052.56303.328810062.57 317.142 10072.6327.1791
 10112.9344.266110133.05354.8194 10153.2363.538410173.35373.875410183.43378.0667
 10193.5380.776710213.74381.490210223.88384.403810244.15386.077610400.95384.0505
#Mann= 3 , 0 , 0
9599.038    0.12       09599.038    0.12       010400.95    0.12       0
#XS Ineff= 2 , 0
       0                               0
Bank Sta=9599.038,10400.95
Exp/Cntr=0.3,0.1

Type RM Length L Ch R = 1 ,6693.902,239.737700,239.737700,239.737700
XS GIS Cut Line= 6
675992.889762742741254.368243371675764.014887779741163.942833464
675623.824584872741100.475611234675557.570371617 741069.99290336
675487.644171878 741039.91543088675252.010786201740947.960176718
#Sta/Elev= 30
9599.022389.2743 9682.77375.81249747.284372.93979855.008371.22619876.962367.2558
9898.916367.76549909.893356.88489931.847330.68029942.824315.74249975.756284.3656
9986.733280.2304    9999278.126510008.71278.460310019.72282.620710030.73 292.863
10052.74298.096110063.75305.912110107.39 318.44810135.18330.593710161.62347.6114
10189.08360.003610204.56364.524510258.23364.916610268.97366.3655 10279.7371.2221
10301.17365.719410333.38363.744510344.11367.695110354.84375.804610400.99377.8745
#Mann= 3 , 0 , 0
9599.022    0.12       09599.022    0.12       010400.99    0.12       0
#XS Ineff= 2 , 0
       0                               0
Bank Sta=9599.022,10400.99
Exp/Cntr=0.3,0.1

Type RM Length L Ch R = 1 ,6454.165,239.737700,239.737700,239.737700
XS GIS Cut Line= 6
676087.151204837741086.264519788675922.240214121740981.911488334
675835.012617873740933.629310531  675753.6292835740896.442154733
675549.938316089740815.114716481675370.816205857740730.142411773
#Sta/Elev= 30
9599.046388.3889 9625.26374.76259648.928370.81099731.765367.43969743.599365.9179
9813.906367.38889871.054366.69249882.484360.67399893.913351.73869904.908345.0183
9948.886333.7565 9959.88318.14249981.869 281.3019992.655274.423910024.84277.5135
10057.02289.645510067.75289.5003 10089.2292.045510121.38301.260710142.95309.9096
 10153.8310.978110164.66319.343810197.23338.050210208.16339.686210219.16344.2308
10241.16 363.58810252.16368.510610285.19372.475310374.11371.757810400.99372.7642
#Mann= 3 , 0 , 0
9599.046    0.12       09599.046    0.12       010400.99    0.12       0
#XS Ineff= 2 , 0
       0                               0
Bank Sta=9599.046,10400.99
Exp/Cntr=0.3,0.1

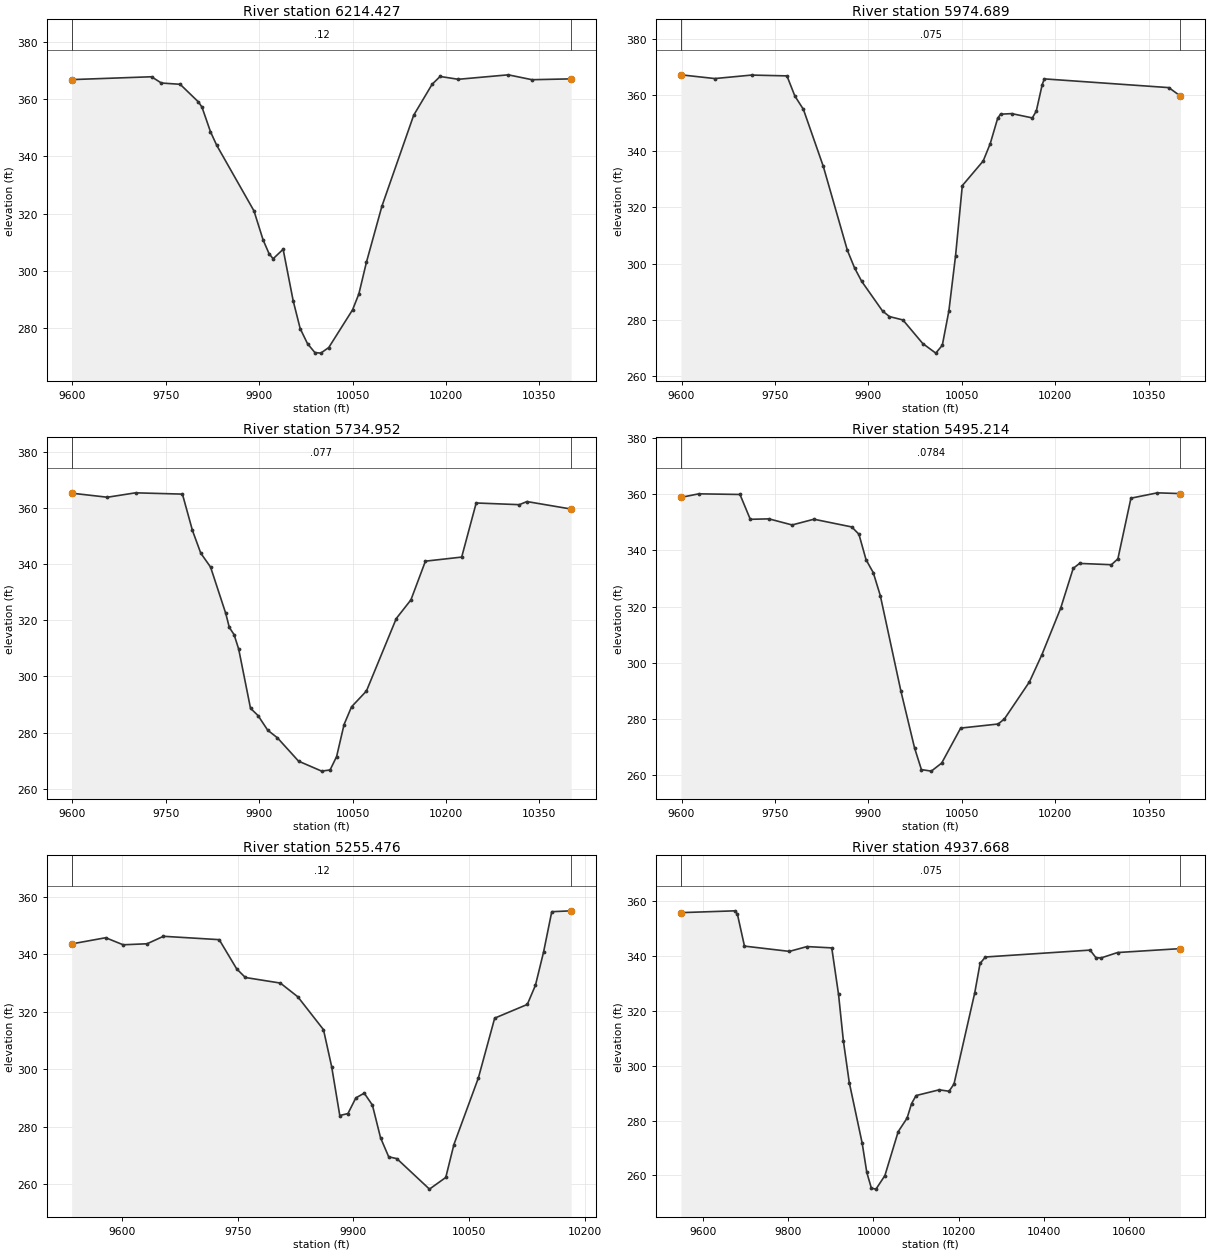
Type RM Length L Ch R = 1 ,6214.427,239.737700,239.737700,239.737700
XS GIS Cut Line= 6
676112.225096267740979.118932721675886.823760701740774.720426669
675786.386137141740625.962516108675720.834674499740549.614236931
675643.598538844740478.324300697675555.643813985740409.162077513
#Sta/Elev= 30
9599.066366.74889727.281367.74379743.167365.55849773.276 365.1189802.614358.9644
9808.296357.16539821.973348.5753 9831.93343.86579891.794320.97919906.425310.8697
  9915.9306.12099922.512304.2882  9938.6307.60489954.733289.62939965.989279.9418
9977.761 274.6839989.534271.6042    9999271.392910011.85273.342310050.11286.5082
10060.21292.0658 10072.3 303.06310097.21322.640910148.15354.311910177.75365.1204
10190.57367.844910219.79366.861410299.99368.418110338.15366.717310400.94367.0106
#Mann= 3 , 0 , 0
9599.066    0.12       09599.066    0.12       010400.94    0.12       0
#XS Ineff= 2 , 0
       0                               0
Bank Sta=9599.066,10400.94
Exp/Cntr=0.3,0.1

Type RM Length L Ch R = 1 ,5974.689,239.737700,239.737700,239.737700
XS GIS Cut Line= 6
676263.360565129  740910.8851042676104.828570712740722.587472742
676020.573897929740526.124634557675979.013079512 740457.25436239
675907.851032299740377.635071173675790.319536946 740279.53212924
#Sta/Elev= 30
9599.072367.12459653.438365.80019712.388367.03469769.224366.74949781.921359.5974
 9795.64  354.859827.635334.54819866.143304.81179877.695 298.5389889.248293.7169
9922.716283.17939933.809281.21369955.433280.00379987.236271.629410008.15268.2181
10018.63271.021210029.12283.154110039.92302.875610050.73 327.74910084.22336.4954
10095.54342.6628 10107.5351.675310112.06353.133610130.07353.341310163.11351.8128
10169.51354.249110178.99363.641510182.38365.683510382.22362.5797 10400.9359.5746
#Mann= 3 , 0 , 0
9599.072   0.075       09599.072   0.075       0 10400.9   0.075       0
#XS Ineff= 2 , 0
       0                               0
Bank Sta=9599.072,10400.9
Exp/Cntr=0.3,0.1

Type RM Length L Ch R = 1 ,5734.952,239.737700,239.737700,239.737700
XS GIS Cut Line= 6
676520.029542359740693.100110911676316.541921353740512.419473193
676271.826640018740474.973858759676230.377166415740442.998744612
676108.385062754740362.140389686675874.092516001740222.397227633
#Sta/Elev= 30
9599.017365.2114  9656.4363.76429701.584365.33349776.889364.87459792.966351.9567
 9806.34343.86379822.073338.90419846.459322.41569852.195317.41639859.832314.8665
9867.257309.69239886.198288.65419898.275286.0664 9913.85280.84449929.467278.1286
9963.348269.833410000.49266.281910013.97266.705310024.43271.453110036.41282.8649
10048.39289.166510072.34294.804310120.25320.600110143.76327.236610167.05 341.011
10225.27342.463710248.56361.721610317.81361.116410330.06362.222610400.98359.5572
#Mann= 3 , 0 , 0
9599.017   0.077       09599.017   0.077       010400.98   0.077       0
#XS Ineff= 2 , 0
       0                               0
Bank Sta=9599.017,10400.98
Exp/Cntr=0.3,0.1

Type RM Length L Ch R = 1 ,5495.214,239.737700,239.737700,239.737700
XS GIS Cut Line= 6
676687.571827868740452.215064276 676489.87970408740306.751213128
676340.687366712740231.838473662676130.657608558 740230.97889106
676043.272642589740211.333502911 675960.94136957740179.703712062
#Sta/Elev= 30
9599.059358.84059627.563360.11469693.795359.88739710.353 351.0589740.298351.2168
9777.506349.05139812.495351.08839873.194348.34589884.707 345.7669896.219336.6634
9907.732332.11959919.064323.92929952.046290.05739974.034269.79269985.027262.0784
   10001261.542710017.57264.411410048.05276.841210108.27278.296610118.31280.1093
10158.45293.275210178.46302.940910208.53319.4319 10228.7333.621910238.87335.3813
10290.06334.916710300.43337.006910321.36358.570510363.89 360.47110400.83360.1906
#Mann= 3 , 0 , 0
9599.059  0.0784       09599.059  0.0784       010400.83  0.0784       0
#XS Ineff= 2 , 0
       0                               0
Bank Sta=9599.059,10400.83
Exp/Cntr=0.3,0.1

Type RM Length L Ch R = 1 ,5255.476,317.808000,317.808000,317.808000
XS GIS Cut Line= 3
676663.969795614740261.067559883676384.382080048740111.954111561
676071.243838519740003.846861511
#Sta/Elev= 30
9534.307343.55499578.472 345.7059601.139343.2533  9632.2343.6032 9653.45346.2038
9725.806345.03479748.472334.8787  9759.7331.88559805.139329.94539827.806325.1724
9861.098313.76049871.677300.94389882.256283.91969892.836284.59629903.125 290.049
9913.994291.67699924.573287.55259935.152276.19019945.732269.56639956.311268.9246
9998.627258.331710019.79262.392210030.36273.8361 10062.1296.981910083.26317.7595
10125.58322.516310136.16329.192310146.74340.781610157.32354.752210182.45355.0543
#Mann= 3 , 0 , 0
9534.307    0.12       09534.307    0.12       010182.45    0.12       0
#XS Ineff= 2 , 0
       0                               0
Bank Sta=9534.307,10182.45
Exp/Cntr=0.3,0.1

Type RM Length L Ch R = 1 ,4937.668,216.244200,216.244200,216.244200
XS GIS Cut Line= 6
676846.766811077740344.041468365676612.681836014 740146.65573588
676561.604864188740066.509283821676492.325444468 739874.39748188
676428.506116708739779.906524296676085.734987127739488.088080364
#Sta/Elev= 30
9548.159355.83889674.906356.50019680.725355.22389697.225343.62879802.771341.7018
9843.861343.45889902.088342.98229918.032325.99379929.386309.01889943.213293.8349
9973.572271.67249984.354261.04949995.135255.297410005.83254.969610026.76259.8922
10058.03275.950410078.88280.875110089.44286.187910100.02289.108510154.21 291.198
10177.36290.680210188.96 293.30410237.68326.577210250.19337.317210262.71  339.66
10508.47342.1726 10522.1339.410410533.78339.292910572.85341.282810720.47342.7179
#Mann= 3 , 0 , 0
9548.159   0.075       09548.159   0.075       010720.47   0.075       0
#XS Ineff= 2 , 0
       0                10110.23       0
Bank Sta=9548.159,10720.47
Exp/Cntr=0.3,0.1