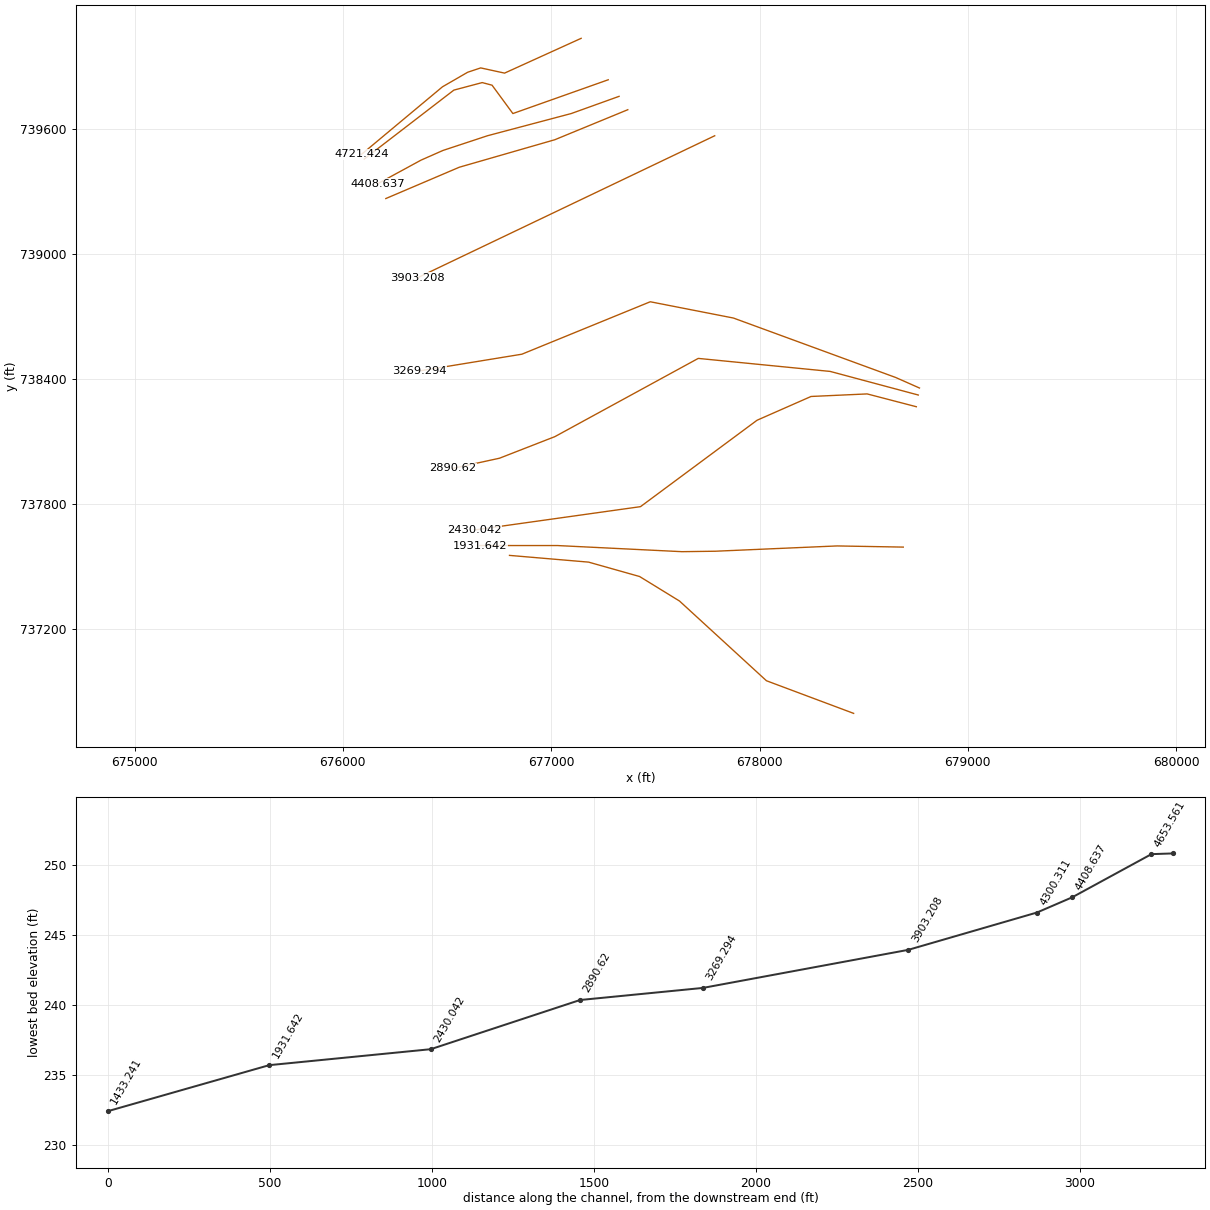
HEC-RAS study 4023_ras.prj: 4023

--- 4023_ras.g01 (geometry) --- (continued)

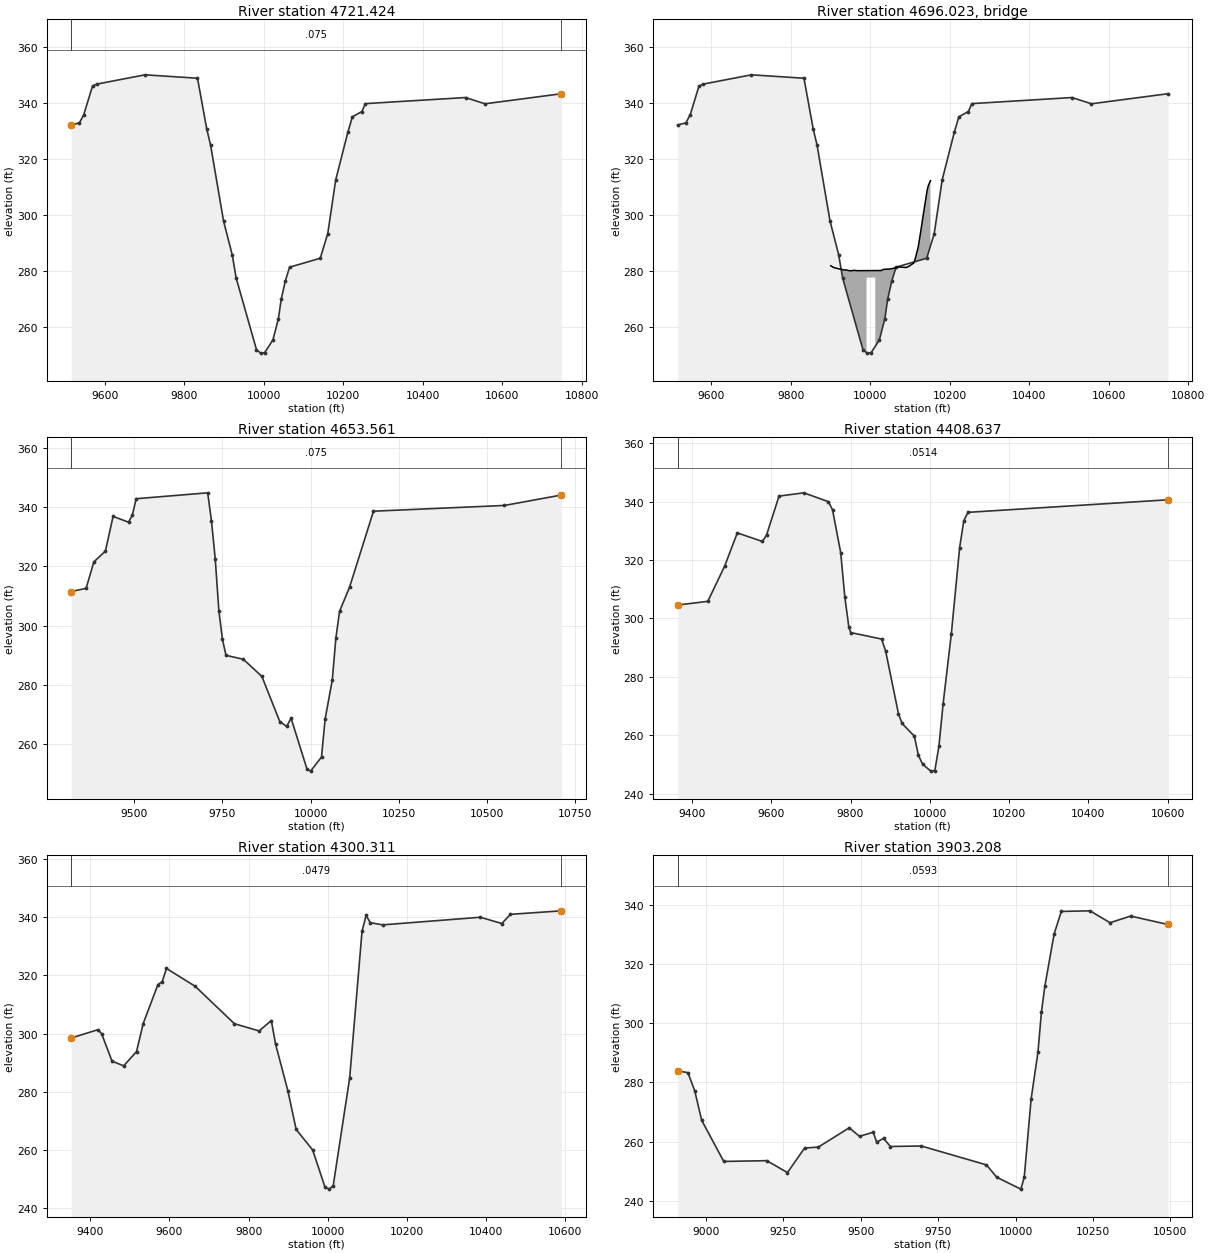
Type RM Length L Ch R = 1 ,4721.424,67.862700,67.862700,67.862700
XS GIS Cut Line= 6
677143.833502888740036.893316221676776.182909012739869.952041745
676661.599575669739894.952041715676599.099575669739874.118708387
676478.266242385 739804.32704173676089.958417008 739480.36939817
#Sta/Elev= 30
9515.682332.0869  9536.4332.80989547.401335.74769569.403345.96899580.404346.6326
9701.414349.91989833.424348.70829856.872330.48679866.203325.01249898.937297.8983
9920.664285.89349930.761277.55159981.668252.13569992.023250.847210002.38250.9995
10023.09255.541410036.96263.120310043.92269.990410054.46276.5689   10065281.4334
10142.22 284.62510161.06 293.36910181.06312.489610211.51329.418510223.06 334.983
10246.91336.859810255.86339.668510507.67 341.83610556.56339.608310749.03343.1941
#Mann= 3 , 0 , 0
9515.682   0.075       09515.682   0.075       010749.03   0.075       0
#XS Ineff= 2 , 0
       0                10045.67       0
Bank Sta=9515.682,10749.03
Exp/Cntr=0.3,0.1

Type RM Length L Ch R = 3 ,4696.023,,,
BEGIN DESCRIPTION:
END DESCRIPTION:
Bridge Culvert--1,0,-1,-1, 0
Deck Dist Width WeirC Skew NumUp NumDn MinLoCord MaxHiCord MaxSubmerge Is_Ogee
19.987800,27.887100,2.6,0, 37, 37, , , 0.95, 0, 0,0,,
 9900.79 9906.75 9912.17 9920.01 9927.41 9933.26 9942.64 9946.52 9954.46 9958.93
 9959.09 9967.35 9990.87 9990.8710012.8510012.8510027.8610033.0910040.5810043.18
10053.2110063.2510069.4510070.5610073.8810085.5010090.2210097.1210108.7310109.87
10113.0610120.9810126.7910133.6010143.1710146.2310151.67
  281.95  281.41  281.15  280.89  280.66  280.48  280.40  280.20  280.17  280.34
  280.34  280.20  280.22  280.22  280.24  280.24  280.25  280.66  280.74  280.74
  280.87  281.21  281.44  281.47  281.50  281.38  281.31  281.72  282.85  282.96
  284.28  288.73  293.81  300.14  308.77  310.49  312.25
 -718.05 -718.59 -718.85 -719.11 -719.34 -719.52 -719.60 -719.80 -719.83 -719.66
 -719.66 -719.80 -719.78  277.72  277.74 -719.76 -719.75 -719.34 -719.26 -719.26
 -719.13 -718.79 -718.56 -718.53 -718.50 -718.62 -718.69 -718.28 -717.15 -717.04
 -715.72 -711.27 -706.19 -699.86 -691.23 -689.51 -687.75
 9900.79 9906.75 9912.17 9920.01 9927.41 9933.26 9942.64 9946.52 9954.46 9958.93
 9959.09 9967.35 9993.58 9993.5810015.5710015.5710027.8610033.0910040.5810043.18
10053.2110063.2510069.4510070.5610073.8810085.5010090.2210097.1210108.7310109.87
10113.0610120.9810126.7910133.6010143.1710146.2310151.67
  281.95  281.41  281.15  280.89  280.66  280.48  280.40  280.20  280.17  280.34
  280.34  280.20  280.22  280.22  280.24  280.24  280.25  280.66  280.74  280.74
  280.87  281.21  281.44  281.47  281.50  281.38  281.31  281.72  282.85  282.96
  284.28  288.73  293.81  300.14  308.77  310.49  312.25
 -718.05 -718.59 -718.85 -719.11 -719.34 -719.52 -719.60 -719.80 -719.83 -719.66
 -719.66 -719.80 -719.78  277.72  277.74 -719.76 -719.75 -719.34 -719.26 -719.26
 -719.13 -718.79 -718.56 -718.53 -718.50 -718.62 -718.69 -718.28 -717.15 -717.04
 -715.72 -711.27 -706.19 -699.86 -691.23 -689.51 -687.75
BR Coef=-1 , 0 , 0 ,, 0 ,,,0.8,0,1,0,
WSPro=,,,, 1 ,,,, 0 ,,,, 0 ,,,,-1 ,-1 ,-1 , 0 , 0 , 0 , 0 , 0
BC Design=,, 0 ,, 0 ,,,,,,

Type RM Length L Ch R = 1 ,4653.561,244.924200,244.924200,244.924200
XS GIS Cut Line= 6
 677273.81745547739838.002208035676816.113464594739675.854819492
676716.113464594739811.965930596676668.891242385739824.465930626
 676532.78013128739788.354819506676102.512051555739457.426548829
#Sta/Elev= 30
 9320.93311.52529363.333 312.6279385.181321.53869417.952325.18899439.799336.9382
9483.494 334.9779494.418337.38059505.342342.91869708.049344.90639718.791335.4501
9729.532322.50729739.858304.9216 9749.92295.38759759.981289.95239809.168 288.625
9861.837282.80259912.584267.53719932.121265.9336 9944.55 268.7019989.562251.5338
9999.907250.794710030.87255.555110041.05 268.363 10061.4281.584410071.57295.6929
   10082304.794810110.52313.037810178.24 338.694 10549.8340.639310711.48344.1721
#Mann= 3 , 0 , 0
 9320.93   0.075       0 9320.93   0.075       010711.48   0.075       0
#XS Ineff= 2 , 0
       0                10032.24       0
Bank Sta=9320.93,10711.48
Exp/Cntr=0.3,0.1

Type RM Length L Ch R = 1 ,4408.637,108.325600,108.325600,108.325600
XS GIS Cut Line= 6
677325.853171531739758.381293091 677095.96136513739675.786718802
676694.134495004739569.274815621676480.597331818739498.731978562
676375.433054325739452.363669533676167.237499027 739339.13521381
#Sta/Elev= 30
9363.788304.55699439.918305.83819482.529 317.9339514.354329.25859577.624326.3219
9588.134328.55179619.543341.85089681.944342.97439744.171339.94279754.496337.1822
9775.147322.51199785.472307.43859795.798 296.9159800.526295.13659878.401292.9172
9888.726288.69339920.981267.31649930.027264.01989961.003259.67819971.329253.0815
9981.654250.1347 10002.3247.707910012.64  247.8910022.98256.197510033.42270.6032
10054.33294.751810075.24324.188810085.69333.396210096.15336.291210600.83340.5911
#Mann= 3 , 0 , 0
9363.788  0.0514       09363.788  0.0514       010600.83  0.0514       0
#XS Ineff= 2 , 0
       0                               0
Bank Sta=9363.788,10600.83
Exp/Cntr=0.3,0.1

Type RM Length L Ch R = 1 ,4300.311,397.103600,397.103600,397.103600
XS GIS Cut Line= 4
 677367.74617206739694.279954925677017.332244605739550.115666464
676558.998911291739418.171222016676206.257666154 739267.82249459
#Sta/Elev= 30
9351.563298.52789419.411301.3867 9428.52299.99829454.803290.57669484.291288.9637
9516.731293.86449533.653303.49789570.797 316.857 9581.61317.86619592.423 322.413
9665.069316.27339764.119303.43669826.555300.94129857.408304.5262 9868.18296.4309
9899.398280.3266 9920.21 267.1199961.835260.10689993.053247.329510003.46246.6267
10013.87 247.81310055.49284.827110086.71335.184910097.11340.652510107.52338.1325
10138.74337.3823 10385.7339.993110440.05337.848310461.79 341.00110590.87342.2008
#Mann= 3 , 0 , 0
9351.563  0.0479       09351.563  0.0479       010590.87  0.0479       0
#XS Ineff= 2 , 0
       09860.397                       0
Bank Sta=9351.563,10590.87
Exp/Cntr=0.3,0.1

Type RM Length L Ch R = 1 ,3903.208,633.914200,633.914200,633.914200
XS GIS Cut Line= 2
677784.951245427739569.206324071676356.240307927738886.488976315
#Sta/Elev= 30
8908.575283.8742 8941.77283.25598963.937277.07718986.103267.19239057.491253.3039
9196.651253.5639 9263.18249.53299318.595257.83439362.927258.14329462.675264.6541
9495.924261.77589540.257263.1746 9551.34259.84189573.506261.07179595.672258.3435
 9695.42258.51999905.998252.13989939.247247.955110016.83243.961410027.91 247.946
10050.08274.321510072.24290.207710083.33303.634710094.41312.395510124.39330.0426
10147.58337.674510240.35337.875210304.99 333.85910371.49336.107410492.03333.2613
#Mann= 3 , 0 , 0
8908.575  0.0593       08908.575  0.0593       010492.03  0.0593       0
#XS Ineff= 2 , 0
       09710.689                       0
Bank Sta=8908.575,10492.03
Exp/Cntr=0.3,0.1

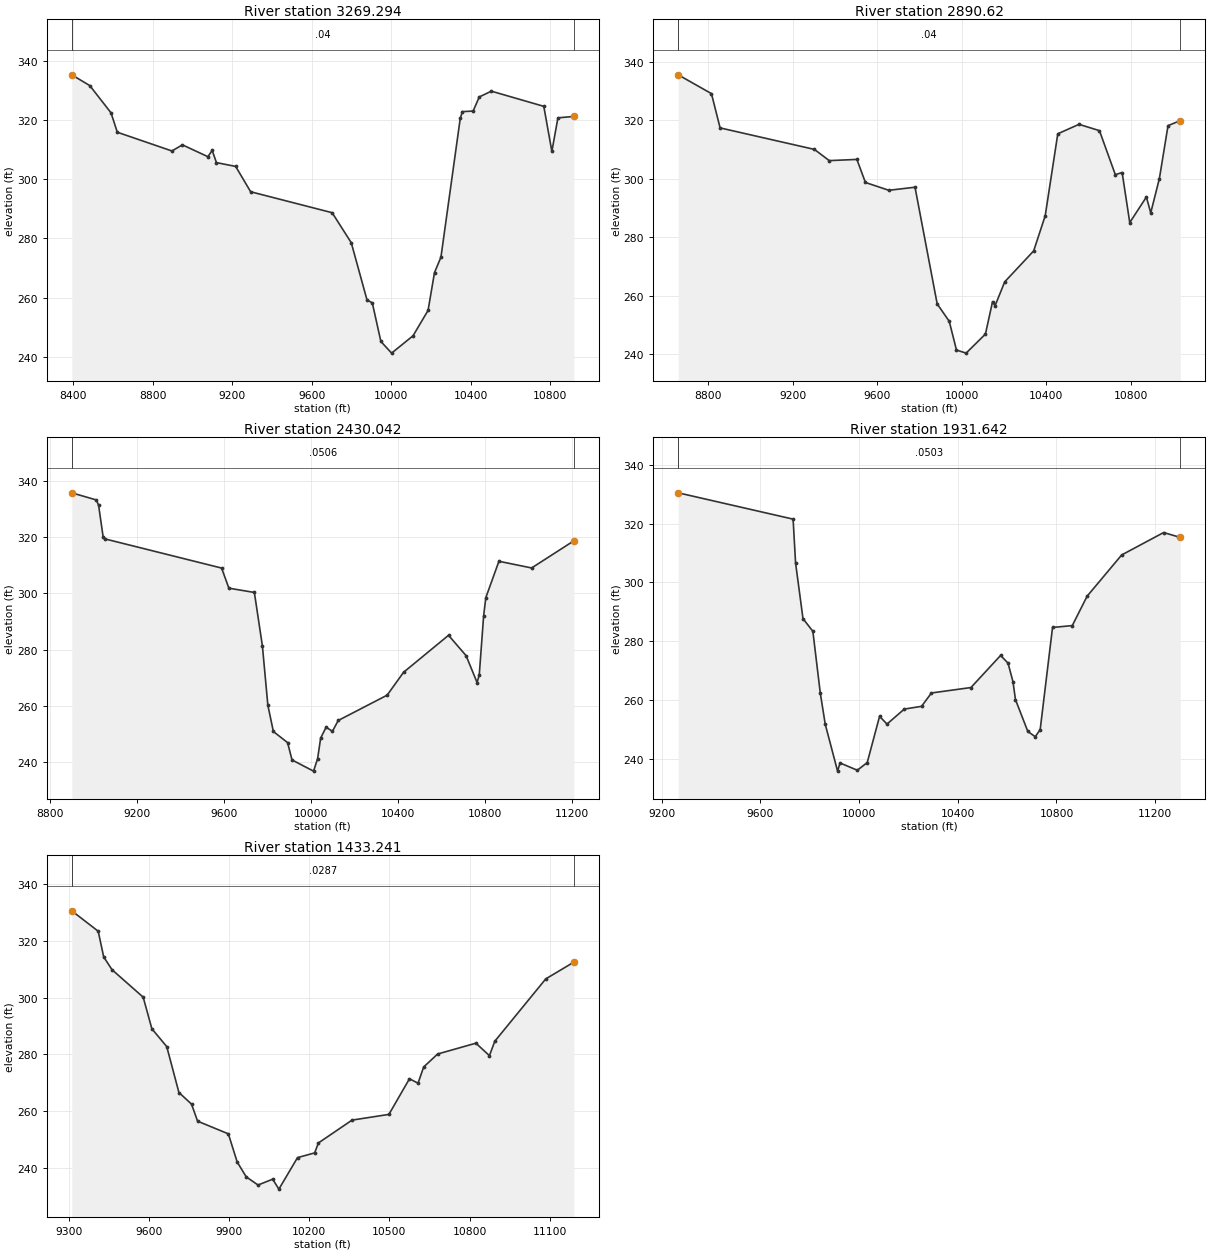
Type RM Length L Ch R = 1 ,3269.294,378.673500,378.673500,378.673500
XS GIS Cut Line= 6
678767.921258569738358.302407011678653.907365888738408.767572656
677874.831436127738694.189445779677475.525880575738772.314445779
676859.206436157738520.578334659676365.251667529738439.899168909
#Sta/Elev= 30
8392.133335.26668482.814331.63288589.695322.43458621.425315.87088896.413309.5417
8949.295311.61069077.622307.60739099.137309.72819120.652305.60719217.471304.3183
9292.774 295.7669703.207288.68549799.409278.55959878.748 259.2099905.415258.2323
9948.623245.182410002.63241.242710110.65247.108710186.27255.685210218.67268.4587
10251.08273.6654 10348.3320.5633 10359.1322.826810413.11323.028110443.96327.7939
 10504.9329.7459   10769324.618910809.63309.3946 10840.1320.732610920.29321.2108
#Mann= 3 , 0 , 0
8392.133    0.04       08392.133    0.04       010920.29    0.04       0
#XS Ineff= 2 , 0
       09755.565                       0
Bank Sta=8392.133,10920.29
Exp/Cntr=0.3,0.1

Type RM Length L Ch R = 1 , 2890.62,460.577900,460.577900,460.577900
XS GIS Cut Line= 6
678762.247784585738324.639794827678339.324032545738437.934239313
677705.990699172738500.434239313677017.654038996738124.837705031
676751.824032545738021.267572656676528.232006282737972.483857825
#Sta/Elev= 30
8659.088335.52858816.214 329.0988857.138317.38329303.237310.03219373.461306.1958
9504.208306.6084 9544.48298.73029655.229  296.059779.157297.10359883.996257.2199
9941.052251.26219975.285241.440810020.93240.380210112.22246.894610145.97257.9794
10157.86256.584610203.51 264.75210340.44275.331310395.09287.351410454.55315.3739
10555.04318.601210651.62316.445110726.75301.389710758.95302.1324   10795285.0011
10873.68293.761610894.15288.325110935.09300.044210976.03318.155511034.14319.8728
#Mann= 3 , 0 , 0
8659.088    0.04       08659.088    0.04       011034.14    0.04       0
#XS Ineff= 2 , 0
       0                               0
Bank Sta=8659.088,11034.14
Exp/Cntr=0.3,0.1

Type RM Length L Ch R = 1 ,2430.042,498.400600,498.400600,498.400600
XS GIS Cut Line= 6
678752.782875538738268.481334448678516.834479302  738329.9356969
678247.446337551738317.675308347677988.173270375 738203.53721033
677428.758507639737788.766173825676631.335982949 737676.78943415
#Sta/Elev= 30
8899.226335.77669012.229333.24329022.595331.35699043.326320.21729053.692319.3653
9588.259  309.04 9621.83 301.8889739.035300.36799775.932  281.389801.041260.2937
9826.369250.95519891.842246.99659912.136240.844910011.17 236.86910029.86 241.296
10043.88248.616110068.89252.471310098.15251.0305 10124.6254.8685 10349.7263.8679
10425.16271.994110631.97285.149810712.82277.893410763.28268.353510773.32271.0711
10793.41292.052810803.46298.524110863.73 311.45111014.25309.072611208.31318.7192
#Mann= 3 , 0 , 0
8899.226  0.0506       08899.226  0.0506       011208.31  0.0506       0
#XS Ineff= 2 , 0
       0                               0
Bank Sta=8899.226,11208.31
Exp/Cntr=0.3,0.1

Type RM Length L Ch R = 1 ,1931.642,498.400700,498.400700,498.400700
XS GIS Cut Line= 6
678690.243203796737594.614385933678372.234507591737600.201723635
677788.049274772737574.784328252677627.473305106 737572.63074927
677030.550070941737602.022315174676657.372447342737602.118819386
#Sta/Elev= 30
9267.415330.44959732.847321.49419742.858306.58139772.895287.64699812.944283.3054
9842.981262.30549863.006251.70989913.067235.7293 9923.08238.50879993.166236.0276
10033.21238.646110083.25254.380510113.28251.740810183.34256.845910253.37257.7877
10293.37262.329610453.45  264.1810573.68275.109810603.74272.484210623.78266.1523
 10633.8260.086210683.89249.240610713.95 247.44110733.99249.858210784.04284.6257
10864.09285.263710924.14295.264711064.15309.300711234.15316.933511301.79315.2664
#Mann= 3 , 0 , 0
9267.415  0.0503       09267.415  0.0503       011301.79  0.0503       0
#XS Ineff= 2 , 0
       0                               0
Bank Sta=9267.415,11301.79
Exp/Cntr=0.3,0.1

Type RM Length L Ch R = 1 ,1433.241,0.000000,0.000000,0.000000
XS GIS Cut Line= 6
678451.875280123736796.403018028678033.324301449736953.045845622
677615.820276408737335.840187923677424.524373966737453.344761614
677179.582702607737522.472341215 676799.90862069737554.786700331
#Sta/Elev= 30
9310.746330.63799409.691323.4467 9430.27314.37399461.415309.86279578.132300.1695
9610.545289.03339666.292282.73599711.882266.53329759.033262.44439781.784256.4159
9896.976251.9487 9930.05242.0167  9963.8236.784910008.09233.890110062.88235.9468
10086.15232.440110155.94243.561310219.97245.215810234.21248.738510360.13256.7954
10498.12258.809210575.02 271.38410607.15269.815310628.26 275.54410680.53280.1164
10823.84283.938210874.39  279.5310894.51284.620311085.27306.619211190.46 312.532
#Mann= 3 , 0 , 0
9310.746  0.0287       09310.746  0.0287       011190.46  0.0287       0
#XS Ineff= 2 , 0
       0                               0
Bank Sta=9310.746,11190.46
Exp/Cntr=0.3,0.1